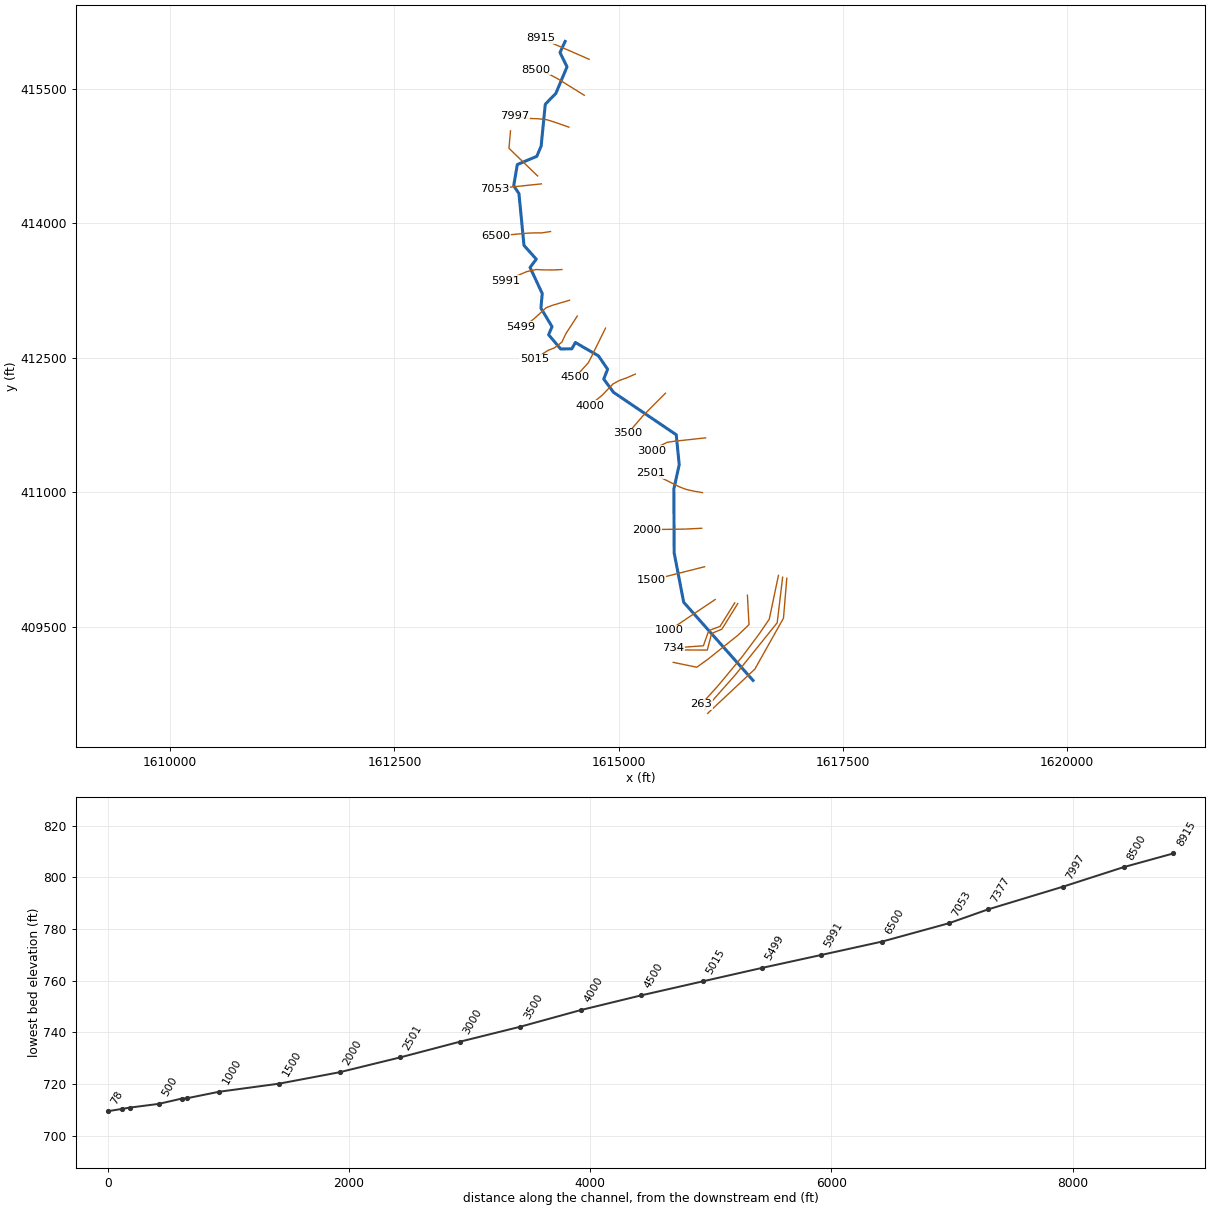
--- LONGRN.prj (project) ---

Proj Title=LONGRN
Current Plan=p01
Default Exp/Contr=0,0
English Units
Geom File=g01
Flow File=f01
Plan File=p01
BEGIN DESCRIPTION:
---------- MODELED AS PART OF WVEMD CTP PROGRAM, 2023----------
Stream Name: Long Run
Flood Zone:  AFH
Wetzel County, WV
HEC-RAS Version: RAS 6.3
Vertical Datum: NAVD88
Projection: NAD 1983 StatePlane West Virginia S FIPS 4702 (US Feet)
Terrain: 1-meter West Virginia FEMA R3 South Central (collected 2018-2020)
Land Use: 2019 NLCD
Hydrologic Method:
WV SIR2010-5033 regression equations
Additional Model Notes:
Leveraged XS
END DESCRIPTION:
DSS Export Rating Curves= 0
DSS Export Rating Curve Sorted= 0
DSS Export Volume Flow Curves= 0
DXF OffsetX= 0
DXF OffsetY= 0
DXF ScaleX= 0
DXF ScaleY= 0

--- LONGRN.p01 (plan) ---

Plan Title=Floodplain
Program Version=6.30
Short Identifier=Floodplain
Geom File=g01
Flow File=f01
Subcritical Flow
K Sum by GR= 0
Std Step Tol= 0.01
Critical Tol= 0.01
Num of Std Step Trials= 20
Max Error Tol= 0.3
Flow Tol Ratio= 0.001
Split Flow NTrial= 30
Split Flow Tol= 0.02
Split Flow Ratio= 0.02
Log Output Level= 0
Friction Slope Method= 1
Unsteady Friction Slope Method= 2
Unsteady Bridges Friction Slope Method= 1
Parabolic Critical Depth
Global Vel Dist= 0 , 0 , 0
Global Log Level= 0
CheckData=True
Encroach Param=-1 ,0,0, 0
Mapping Interval=1HOUR
Computation Time Step Use Courant=        0
Computation Time Step Use Time Series=    0
Computation Time Step Count To Double=0
Computation Time Step Max Doubling=0
Computation Time Step Max Halving=0
Computation Time Step Residence Courant=0
Run HTab= 0
Run UNet= 0
Run Sediment= 0
Run PostProcess= 0
Run WQNet= 0
Run RASMapper= 0
UNET Theta= 0
UNET Theta Warmup= 0
UNET ZTol= 0
UNET ZSATol= 0
UNET MxIter= 0
UNET Max Iter WO Improvement= 0
UNET MaxInSteps= 0
UNET DtIC= 0
UNET DtMin= 0
UNET MaxCRTS= 0
UNET WFStab= 0
UNET SFStab= 0
UNET WFX= 1
UNET SFX= 1
UNET Gravity=32.17405
UNET 1D Methodology=Finite Difference
UNET DSS MLevel= 1
UNET Pardiso=0
UNET DZMax Abort= 0
UNET Use Existing IB Tables= 0
UNET Froude Reduction=False
UNET Froude Limit= 0
UNET Froude Power= 0
UNET D1 Cores= 0
UNET WindReference=Eulerian
UNET WindDragFormulation=Hsu (1988)
UNET D2 Coriolis=0
UNET D2 Cores= 0
UNET D2 Theta= 1
UNET D2 Theta Warmup= 1
UNET D2 Z Tol= 0.01
UNET D2 Volume Tol= 0.01
UNET D2 Max Iterations= 20
UNET D2 Equation= 0
UNET D2 RampUpFraction=0.1
UNET D2 TimeSlices= 1
UNET D2 Turbulence Formulation=Non-Conservative (original)
UNET D2 Eddy Viscosity=0.3
UNET D2 Transverse Eddy Viscosity=0.1
UNET D2 Smagorinsky Mixing=0
UNET D2 BCVolumeCheck=0
UNET D2 Cores=0
UNET D2 SolverType=PARDISO (Direct)
UNET D2 Minimum Iterations= 3
UNET D2 Maximum Iterations= 30
UNET D2 Restart Number= 10
UNET D2 Relaxation Coeff=1.3
UNET D2 SOR Precondition Iterations= 10
UNET D2 ILUT Maximum Fill= 8
UNET D2 ILUT Tolerance=1E-08
UNET D2 Convergence Tolerance=0.00001
UNET D1D2 MaxIter= 0
UNET D1D2 ZTol=0.01
UNET D1D2 QTol=0.1
UNET D1D2 MinQTol=1
Write IC File= 0
Write IC File at Fixed DateTime=0
Write IC File at Sim End=0
Echo Input=False
Echo Parameters=False
Echo Output=False
Write Detailed= 0
HDF Write Warmup=0
HDF Write Time Slices=0
HDF Flush=0
HDF Compression= 1
HDF Chunk Size= 1
HDF Spatial Parts= 1
HDF Use Max Rows=0
HDF Fixed Rows= 1
Calibration Method= 0
Calibration Iterations= 20
Calibration Max Change=0.05
Calibration Tolerance=0.2
Calibration Maximum=1.5
Calibration Minimum=0.5
Calibration Optimization Method= 1
WQ AD Non Conservative
WQ ULTIMATE=-1
WQ Max Comp Step=1HOUR
WQ Output Interval=15MIN
WQ Output Selected Increments= 0
WQ Output face flow=0
WQ Output face velocity=0
WQ Output face area=0
WQ Output face dispersion=0
WQ Output cell volume=0
WQ Output cell surface area=0
WQ Output cell continuity=0
WQ Output cumulative cell continuity=0
WQ Output face conc=0
WQ Output face dconc_dx=0
WQ Output face courant=0
WQ Output face peclet=0
WQ Output face adv mass=0
WQ Output face disp mass=0
WQ Output cell mass=0
WQ Output cell source sink temp=0
WQ Output nsm pathways=0
WQ Output nsm derived pathways=0
WQ Create Restart=0
WQ Fixed Restart=0
WQ System Summary=0
WQ Write To DSS=0
Sorting and Armoring Iterations= 10
XS Update Threshold= 0.02
Bed Roughness Predictor= 0
Hydraulics Update Threshold= 0.02
Energy Slope Method= 1
Volume Change Method= 1
Sediment Retention Method= 0
Sediment TS Multiplier= 1
Warm Up Method= 0
XS Weighting Method= 0
Number of US Weighted Cross Sections= 1
Number of DS Weighted Cross Sections= 1
Upstream XS Weight=0
Main XS Weight=1
Downstream XS Weight=0
Number of DS XS's Weighted with US Boundary= 1
Upstream Boundary Weight= 1
Weight of XSs Associated with US Boundary= 0
Number of US XS's Weighted with DS Boundary= 1
Downstream Boundary Weight= 0.5
Weight of XSs Associated with DS Boundary= 0.5
Percentile Method= 0
Sediment Output Level= 3
Mass or Volume Output= 0
Output Increment Type= 1
Profile and TS Output Increment= 1
Transport Output Increment 1
XS Output Flag= 0
XS Output Increment= 10
Read HDF5 Sediment Hotstart= 0
Sediment Hotstart Type= 0
Write Gradation File= 0
Read Gradation Hotstart= 0
Write HDF5 File= 1
Write Binary Output= 1
Write DSS Sediment File= 0
DSS Sediment Output Type= 1
SV Curve= 0
Specific Gage Flag= 0
Subcell Erosion Methods= 0
Subcell Deposition Methods= 0
Advection Scheme= 1
Matrix Solver= 0
Implicit Weighting Factor= 1
Maximum Outer Loop Convergence Iterations= 5
Convergence Maximum Absolute= 0.001
Convergence RMSE= 0.0001
Grain Fractions Max Abs Error= 0.001
Max Subgrid Regions= 1
Max Subgrid Length Scale= 3.402823E+38
Initial Layer Thickness= 3.402823E+38
Min Layer Thickness= 3.402823E+38
Max Layer Thickness= 3.402823E+38
Number of Layers= 5

--- LONGRN.f01 (steady flow) ---

Flow Title=Flow
Program Version=4.00
Number of Profiles=1
Profile Names=F01pct
River Rch & RM=LONGRN,Main,8915
     823
River Rch & RM=LONGRN,Main,6500
     946
River Rch & RM=LONGRN,Main,3500
    1100
Boundary for River Rch & Prof#=LONGRN,Main      ,1
Up Type=0
Dn Type=3
Dn Slope=0.008319

--- LONGRN.g01 (geometry) ---

Geom Title=Geometry
Program Version=6.31

River Reach=LONGRN          ,Main
Reach XY= 30
1614403.91665843416029.045790117     1614346.626      415904.603
       1614424.8      415745.296     1614299.721      415448.235
     1614182.671      415328.649     1614136.189      414861.294
     1614088.017      414747.625     1613870.819      414656.351
     1613830.675      414420.561     1613888.989        414331.4
      1613945.19      413754.178     1614082.101       413601.21
       1614012.8      413508.669     1614148.443      413217.945
     1614134.076      413055.258     1614257.887      412848.202
     1614219.434      412758.619     1614354.231      412600.158
     1614478.888      412601.848     1614517.341      412671.994
     1614774.259      412524.096     1614877.365      412374.509
     1614834.264      412264.642      1614942.44      412117.168
     1615642.627      411643.474     1615675.587      411310.072
     1615616.006      411039.209     1615619.254      410327.084
     1615725.555       409776.14     1616498.517      408904.867

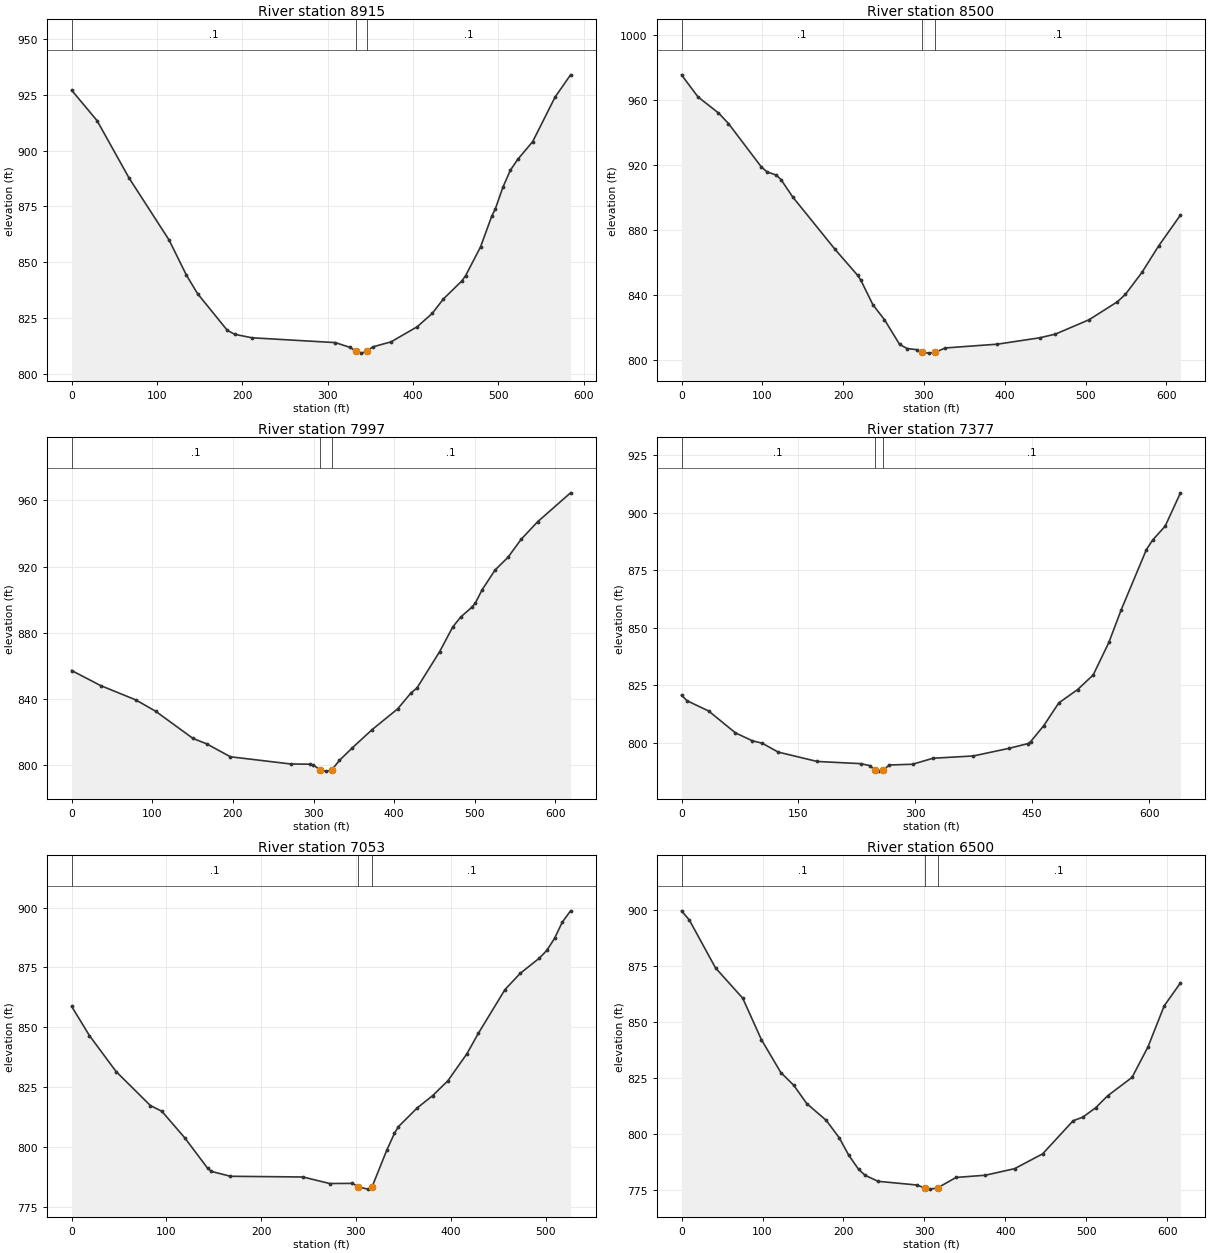
Type RM Length L Ch R = 1 ,8915    ,416.5,414.1,412.3
XS GIS Cut Line= 2
1614671.46027884 415829.608565331614135.35630739 416063.08936037
#Sta/Elev= 30
       0  927.01    29.8   913.4    67.4  887.65   114.2  859.95   134.5  844.25
   147.6  835.93   182.5  819.48   191.3  817.71   211.4  816.17   309.1  814.01
   326.5  811.84   333.2  810.13   339.6   809.3  346.02810.1831   352.7  812.06
   374.5  814.38     405  821.12   422.5  827.05   435.6  833.52   457.4  841.65
   461.8  844.05   479.2  856.85   492.3  870.59   496.7  874.04   505.4  883.58
   514.1  891.15   522.8  896.05   540.3  903.99   566.5  923.89   584.7  933.89
#Mann= 3 ,-1,0
       0      .1       0   333.2    .045       0  346.02      .1       0
Bank Sta=333.2,346.02
XS Rating Curve= 0 ,0
Exp/Cntr(USF)=0,0
Exp/Cntr=0.3,0.1

Type RM Length L Ch R = 1 ,8500    ,500.6,503.8,506.6
XS GIS Cut Line= 6
1614617.48487192415428.451921418 1614463.4402325415523.959932506
1614314.70693417415616.1739869271614248.26513793415651.340911344
1614168.99265867415689.4057958421614073.81699601415713.010079339
#Sta/Elev= 30
       0  975.28    20.4  961.68    45.7  951.84    58.1   945.3    98.8  918.58
   105.6  915.62   117.3  913.55   123.1  910.81   137.6  900.11   189.9   867.9
   218.1  851.76   221.9  848.85   236.9  833.67   251.1  824.59   269.9  809.32
   279.3  806.79   291.6  806.07   298.1  804.54   306.1  803.97  314.19  804.54
   326.4  807.15   390.9  809.49   443.4  813.42   462.7  815.69   504.4  824.55
   539.2  835.54   549.2   840.1   569.7  853.64   590.3  869.88   617.4  888.99
#Mann= 3 ,-1,0
       0      .1       0   298.1    .045       0  314.19      .1       0
Bank Sta=298.1,314.19
XS Rating Curve= 0 ,0
Exp/Cntr(USF)=0,0
Exp/Cntr=0.3,0.1

Type RM Length L Ch R = 1 ,7997    ,622.1,619.8,613
XS GIS Cut Line= 6
1614446.24013567415073.0369498431614271.98490676415133.549624085
1614198.39253426415155.9416396771614098.37370542415166.730660096
1614023.41322543415169.1650384221613843.67113084415195.434999004
#Sta/Elev= 30
       0  857.21    36.2  848.06    79.6  839.44   104.1  832.62   150.5  816.15
   167.4   812.9   196.9  805.07   271.7  800.71   295.9  800.57   299.9  800.06
   307.9  797.13     316  796.39  322.61797.1408   332.1  802.89   347.5   810.2
   372.3  821.35   404.3  834.03   420.3  843.37   428.3   846.7   456.4  868.65
   472.6  883.52   482.4  889.48   496.8  895.69   500.8  898.16   508.8  905.81
     525  917.91   541.2  925.69   557.4  936.51   577.9  947.14   618.7  964.61
#Mann= 3 ,-1,0
       0      .1       0   307.9    .045       0  322.61      .1       0
Bank Sta=307.9,322.61
XS Rating Curve= 0 ,0
Exp/Cntr(USF)=0,0
Exp/Cntr=0.3,0.1

Type RM Length L Ch R = 1 ,7377    ,318.1,323.6,328.5
XS GIS Cut Line= 3
 1614097.3739198414528.4746369791613777.46809631414837.196460803
1613794.72653903415032.008388771
#Sta/Elev= 30
       0  820.63     7.3  818.19    34.9  813.74    69.2  804.25    90.7  800.84
   103.8  799.72     124   795.9   174.1  791.82   229.7  790.88   241.4  790.03
   247.8  788.22   253.5  787.62  258.94  788.23   266.8  790.28   296.4  790.61
   322.7  793.22   374.5  794.22   420.6  797.56   444.6   799.6   447.9  800.42
   464.9  807.44   484.1  817.29   508.2  823.07   528.2  829.43   548.3  843.55
   564.3  857.88   596.5  883.95   604.5  888.09   620.6  894.15   640.2  908.61
#Mann= 3 ,-1,0
       0      .1       0   247.8    .045       0  258.94      .1       0
Bank Sta=247.8,258.94
XS Rating Curve= 0 ,0
Exp/Cntr(USF)=0,0
Exp/Cntr=0.3,0.1

Type RM Length L Ch R = 1 ,7053    ,552.2,553,552
XS GIS Cut Line= 2
1614138.83074532414440.5357568571613615.27899424414385.443183824
#Sta/Elev= 30
       0  858.75    18.8  846.51      47  831.43    83.2  817.22    95.2  814.85
   119.4  803.73   143.5  791.02   147.5  789.69   167.6  787.65   244.1  787.36
   272.2  784.63   296.3  784.68  302.52  783.23   312.4  782.28  316.97  783.23
   332.5  798.56   340.6  805.63   344.6  808.34   364.7  816.29   380.8  821.36
   396.9  827.57     417  838.88   429.1  847.44   457.2  865.75   473.3  872.54
   493.4  878.87   501.5  882.22   509.5  887.17   517.6  893.91   526.4  898.69
#Mann= 3 ,-1,0
       0      .1       0  302.52    .045       0  316.97      .1       0
Bank Sta=302.52,316.97
XS Rating Curve= 0 ,0
Exp/Cntr(USF)=0,0
Exp/Cntr=0.3,0.1

Type RM Length L Ch R = 1 ,6500    ,505.7,509,509
XS GIS Cut Line= 6
  1614241.592251413909.2394086721614145.82899109413894.516997173
 1614057.9945211413894.0022344291613982.98450051413890.712214753
1613883.37511967413881.8769305941613628.17713925413858.681110844
#Sta/Elev= 30
       0  899.73     9.6  895.65      42  874.18    75.6  860.62    98.6  842.13
   122.6  827.38   138.6  821.66   154.6  813.49   178.6     806   194.6  798.26
   206.6   790.3   218.6  784.09   226.6   781.4   242.7  778.69   290.8  777.03
  300.07  775.73   306.9  775.19   316.1  775.73     339  780.42   375.2  781.41
   411.3  784.35   445.9  790.98   483.6   805.8   495.6  807.41   511.7   811.7
     526  816.91   556.3  825.19     576  838.86     596   857.2   616.1  867.48
#Mann= 3 ,-1,0
       0      .1       0  300.07    .045       0   316.1      .1       0
Bank Sta=300.07,316.1
XS Rating Curve= 0 ,0
Exp/Cntr(USF)=0,0
Exp/Cntr=0.3,0.1

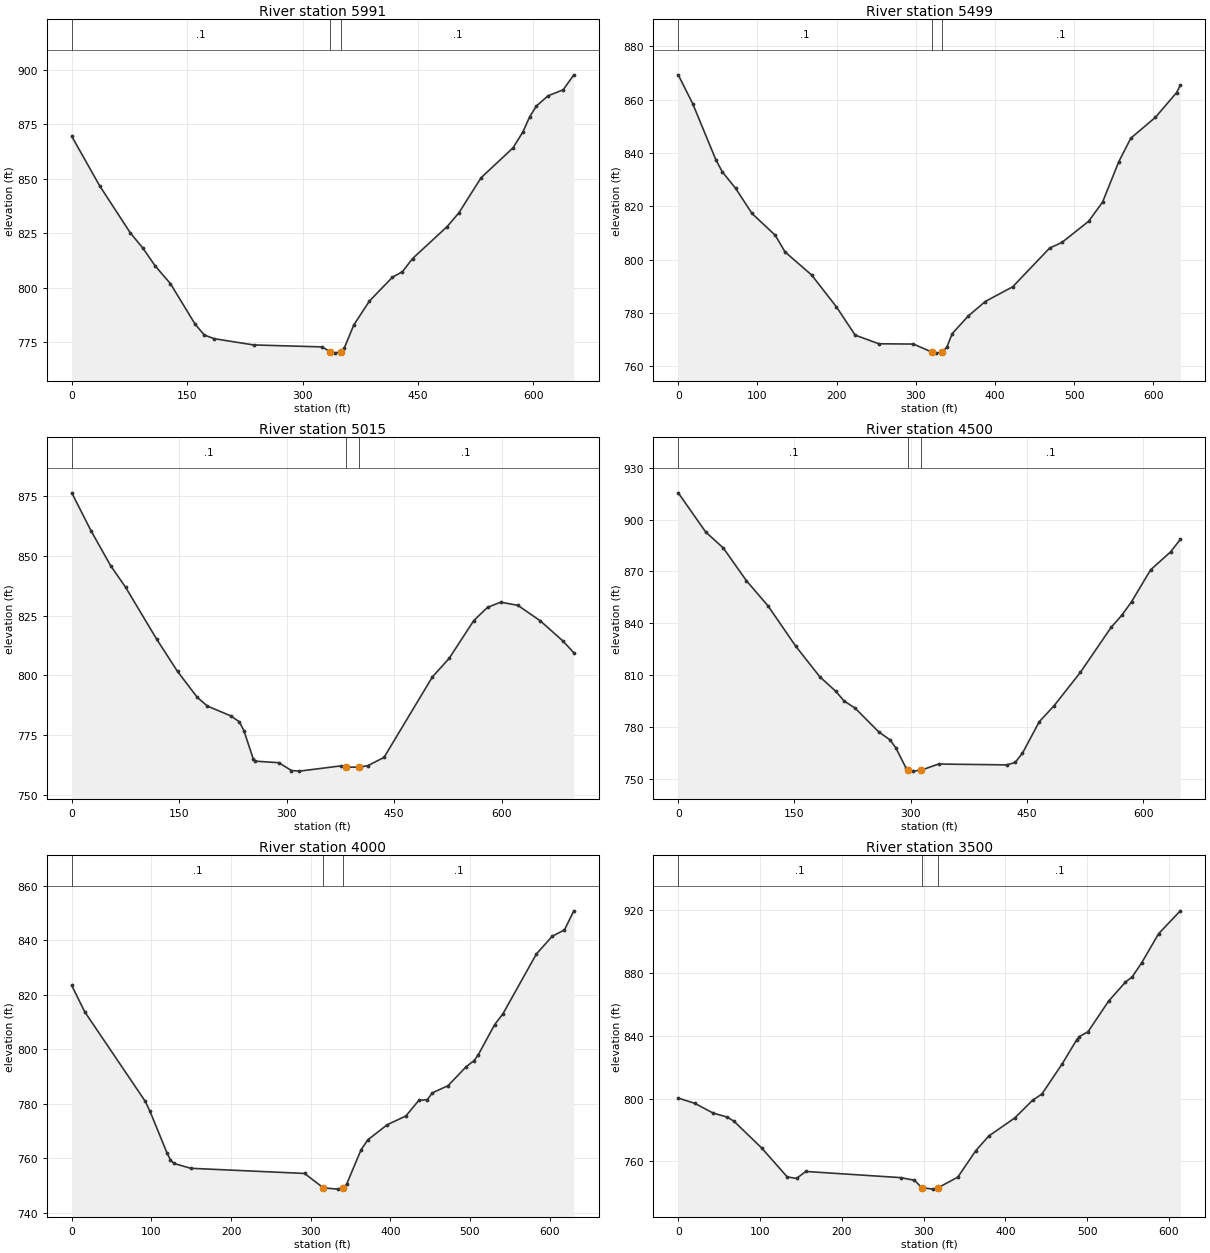
Type RM Length L Ch R = 1 ,5991    ,489.2,492.3,495.8
XS GIS Cut Line= 6
1614368.31968784413485.3957681661614265.77264884413480.657588676
1614167.09043151413481.3314718461614079.81370318413485.931856334
1613974.90019909413462.0034265071613739.36720559413361.066948593
#Sta/Elev= 30
       0  869.49    36.2  846.81    76.3  825.06    92.3  818.25   108.3  810.05
   128.3  801.84   160.3  783.26   172.3  778.27     185   776.6   236.4  773.72
   325.4  772.82  335.53770.6696   341.8  769.96   350.3  770.64   354.1  772.19
   366.5  782.84   386.9  793.88   416.8   804.8   429.8  807.36   442.9  813.36
   487.9  828.05   503.2  834.39   532.1  850.52   573.5  864.18   586.5  871.61
   595.2  878.47   603.9  883.39   618.9  888.08   638.7  890.85   652.6  897.73
#Mann= 3 ,-1,0
       0      .1       0  335.53    .045       0   350.3      .1       0
Bank Sta=335.53,350.3
XS Rating Curve= 0 ,0
Exp/Cntr(USF)=0,0
Exp/Cntr=0.3,0.1

Type RM Length L Ch R = 1 ,5499    ,482,484.4,481.5
XS GIS Cut Line= 6
     1614453.706413143.2629222571614267.61089976413088.548792839
1614192.34563035413060.2109230011614063.26977301 412941.79678975
1613994.85586785412886.9376475071613907.82356159412845.017127678
#Sta/Elev= 30
       0   869.3    18.3  858.47    47.4  837.52    55.7  832.89    72.4  826.77
    93.1  817.32   122.4  809.17   134.9  802.88   168.4  794.24   199.8  782.26
   223.4  771.69   253.3  768.45     297  768.34  320.42765.2953   325.3  764.94
   333.1   765.3   339.2  767.21   345.9  772.25     366  778.81   387.6  784.29
   422.3  789.82     469  804.36   484.4  806.43   518.2   814.4   535.7  821.55
   556.1  836.65   571.4  845.54   602.5  853.37   629.1   862.6   633.9   865.4
#Mann= 3 ,-1,0
       0      .1       0  320.42    .045       0   333.1      .1       0
Bank Sta=320.42,333.1
XS Rating Curve= 0 ,0
Exp/Cntr(USF)=0,0
Exp/Cntr=0.3,0.1

Type RM Length L Ch R = 1 ,5015    ,508.7,514.2,516
XS GIS Cut Line= 6
1614539.13266642412966.5526457581614412.35995409412770.884073839
1614366.89679043412675.0906302481614284.69026193412612.477238417
1614214.90923351412584.9894324991614060.27732493412487.155966759
#Sta/Elev= 30
       0  876.48    26.8  860.61    54.2  845.97    75.2  836.86   118.6  815.09
   147.7  801.58   175.3   790.7   189.3  787.09     222  782.97   233.9   780.5
   240.3  776.79   253.2  765.08   256.2  763.99     289  763.34   306.7  760.07
   317.8  759.81   376.5  762.04     383  761.47  400.49  761.47   413.2  762.09
   435.9  765.56   503.5  799.34   526.8  807.07   561.2  822.93   580.4  828.48
   598.8  830.65   622.8   829.3   654.1  822.81   685.7  814.36   700.9  809.42
#Mann= 3 ,-1,0
       0      .1       0     383    .045       0  400.49      .1       0
Bank Sta=383,400.49
XS Rating Curve= 0 ,0
Exp/Cntr(USF)=0,0
Exp/Cntr=0.3,0.1

Type RM Length L Ch R = 1 ,4500    ,501.7,500,500.4
XS GIS Cut Line= 6
1614854.16320434412832.3941214231614773.94912593412669.860325754
1614696.50177425412512.9308495821614662.46476884412446.092400596
1614597.59186709412375.2615054991614519.28362475412283.599615335
#Sta/Elev= 30
       0  915.45    35.5  892.73    58.2  883.51      88  864.56   115.8  850.05
   151.5  826.75   182.7  808.96   203.5  800.48   213.9  795.01   228.4  790.76
   258.6  777.11   273.2  772.47   280.9  767.74   294.2  755.91   297.1  754.93
   302.9  754.34  313.71  754.93   335.9  758.44     424  757.96   434.7  759.34
   444.2  764.74   465.9  782.95     485   792.2     519  811.57   558.7  837.62
   572.7  844.74     585  852.43   609.6   870.9   635.3  881.24   647.9  888.48
#Mann= 3 ,-1,0
       0      .1       0   297.1    .045       0  313.71      .1       0
Bank Sta=297.1,313.71
XS Rating Curve= 0 ,0
Exp/Cntr(USF)=0,0
Exp/Cntr=0.3,0.1

Type RM Length L Ch R = 1 ,4000    ,500.6,500.4,500.4
XS GIS Cut Line= 6
1615186.14908892412320.035566092 1615091.8546581412278.736764178
1615005.11270559412247.3952914181614937.30247375412209.685393095
1614815.71971168412083.7309205831614674.99295901411967.427675501
#Sta/Elev= 30
       0  823.44    16.3  813.76    92.3   780.9    98.3  777.19   119.7  761.87
   123.9  759.42   128.2   758.1   149.4  756.31   292.3  754.42     316  749.12
   333.8  748.66  341.12 749.116   345.2  750.51   363.4  763.18   371.9  766.78
   396.1   772.3   419.6  775.53   435.7  781.21   446.7  781.55   452.7     784
   472.6  786.67   495.3  793.62   504.9  795.79   510.1  797.79     531  809.06
   541.4  813.02   583.4  834.98   603.3  841.52   618.7  843.85   630.5  850.86
#Mann= 3 ,-1,0
       0      .1       0     316    .045       0  341.12      .1       0
Bank Sta=316,341.12
XS Rating Curve= 0 ,0
Exp/Cntr(USF)=0,0
Exp/Cntr=0.3,0.1

Type RM Length L Ch R = 1 ,3500    ,504.5,499.6,492.9
XS GIS Cut Line= 6
1615522.41350825412106.7846802621615341.21767643411925.588848427
1615271.09150434411854.2933873391615221.66345359411797.514957592
1615164.41389617411730.5452752561615102.85299568411659.039840832
#Sta/Elev= 30
       0  800.29    20.2  796.94    42.8  790.69    59.8  788.19    68.3  785.47
   102.2  768.38   133.3  750.01   144.7  749.07     156   753.5   271.9  749.57
   288.9  747.88   297.8  743.18   311.5  742.23  317.96743.1856   341.9  749.88
   363.9  766.78   379.8   776.1   411.6  787.62   433.3  798.89   444.7  802.85
   469.7  822.23   487.2  837.38   490.7  839.54   501.2  842.61   526.2  862.06
   546.8  874.17   555.3  877.64   566.7  886.51   587.5   905.1     614  919.67
#Mann= 3 ,-1,0
       0      .1       0   297.8    .045       0  317.96      .1       0
Bank Sta=297.8,317.96
XS Rating Curve= 0 ,0
Exp/Cntr(USF)=0,0
Exp/Cntr=0.3,0.1

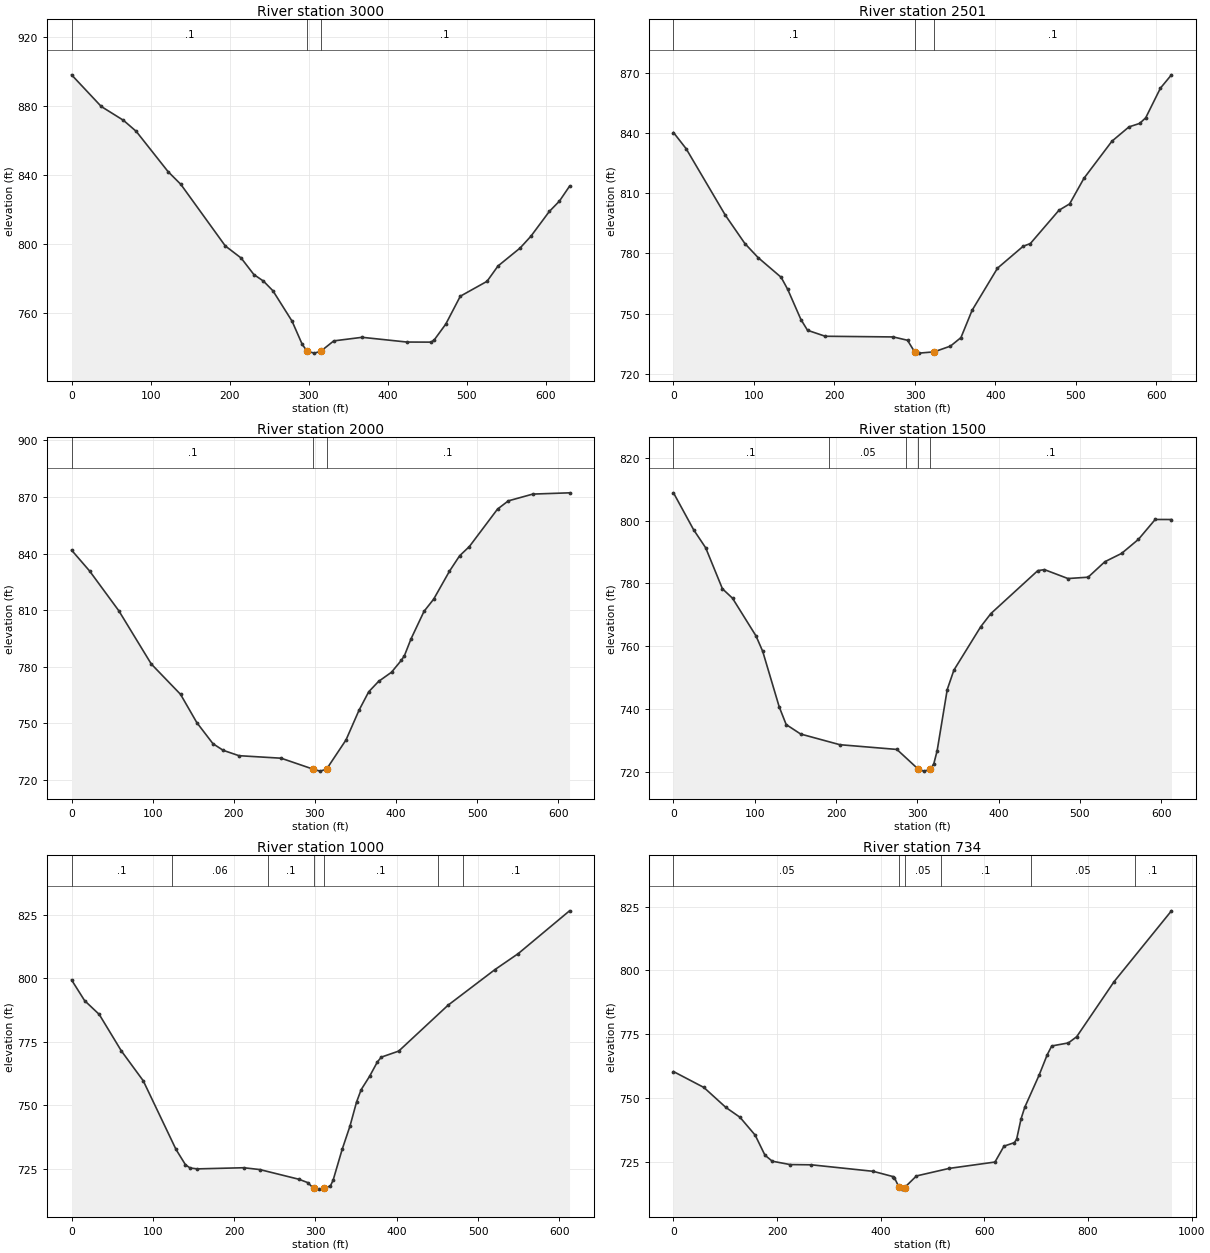
Type RM Length L Ch R = 1 ,3000    ,504.5,499.3,492.1
XS GIS Cut Line= 6
1615969.45329659411609.060610086 1615876.2563045411598.893635675
 1615615.3043986411570.4255167541615541.12344459411558.839581922
1615456.84146093411518.2192563411615366.00305992411465.196068421
#Sta/Elev= 30
       0  898.12    37.6  879.72    65.7  871.68    81.8  865.29   122.1  841.89
   138.2  834.52   194.5  798.73   214.6  791.68   230.7  782.08   242.8  778.29
   254.8  772.67     279  755.02   291.9  741.49  298.12737.5608   307.2  736.44
  315.41  737.56   331.8  743.55   367.6  745.63   424.3  742.88   455.1  742.83
   459.1  744.23   473.5  753.29   491.9   769.5   525.7  778.15   539.6  787.06
   567.6  797.51   581.3  804.39   604.5  818.72   617.3  824.74   630.1  833.39
#Mann= 3 ,-1,0
       0      .1       0  298.12    .045       0  315.41      .1       0
Bank Sta=298.12,315.41
XS Rating Curve= 0 ,0
Exp/Cntr(USF)=0,0
Exp/Cntr=0.3,0.1

Type RM Length L Ch R = 1 ,2501    ,495.5,500.7,506.5
XS GIS Cut Line= 6
1615935.58459793410998.576922923  1615841.242595411014.340670928
1615754.73686251411033.8294770871615684.34822376411059.997731835
1615448.04521868411177.3593737481615359.40497601411212.261206836
#Sta/Elev= 30
       0  840.28    15.7  832.22    64.4  799.07    88.7  784.94     105  777.98
   133.7  768.13   141.9  762.09   158.3  747.07   166.5  741.71   188.5  738.73
     273  738.39   290.7  736.73   299.5  730.98     305  730.32  323.78730.9543
   344.1  733.83   357.1  738.06   370.9  751.63   402.5  772.67   434.4  783.59
   443.3  784.93   478.8  801.51   492.1  804.71   509.9  817.47   544.7  835.97
   565.8  843.08   579.1  844.82   586.6  847.61   604.9   862.4   618.6  869.04
#Mann= 3 ,-1,0
       0      .1       0   299.5    .045       0  323.78      .1       0
Bank Sta=299.5,323.78
XS Rating Curve= 0 ,0
Exp/Cntr(USF)=0,0
Exp/Cntr=0.3,0.1

Type RM Length L Ch R = 1 ,2000    ,498.4,500,501.9
XS GIS Cut Line= 6
1615926.31427525410601.1170879161615831.71407075 410596.62004967
1615743.76542775410592.0252425821615668.77771685410590.532463416
1615568.78513467410589.3280695081615312.55369176410586.240805343
#Sta/Elev= 30
       0  841.81    22.2  830.76    58.3  809.62    98.3  781.41   134.4  765.31
   154.4  750.36   174.4  739.12     187  735.63   206.4  732.79   258.4  731.45
  298.04  725.62   306.4   724.6  314.37  725.62   338.4  741.14   354.4  756.85
   366.4  766.68   378.5  772.16   394.5  777.05   406.7  783.41   410.5   785.9
   418.5  794.68   434.6  809.34   446.5   815.8   465.9  830.58   478.5  838.81
   490.5  843.69   525.2  863.55   538.5  867.92   568.7  871.52     614  872.19
#Mann= 3 ,-1,0
       0      .1       0  298.04    .045       0  314.37      .1       0
Bank Sta=298.04,314.37
XS Rating Curve= 0 ,0
Exp/Cntr(USF)=0,0
Exp/Cntr=0.3,0.1

Type RM Length L Ch R = 1 ,1500    ,498.6,500.5,502.8
XS GIS Cut Line= 6
1615958.50810851410172.1868434251615867.62180734410149.191810668
1615782.79487726410127.729583249  1615613.140689410084.805456504
1615540.43184492 410066.409495921615364.71861367410021.952891916
#Sta/Elev= 30
       0  808.86    24.7  797.12    39.6  791.34    60.2  778.28    72.6  775.28
   101.5  763.26   109.7  758.38   130.1  740.61   138.6  735.03   156.4  732.01
   204.6  728.61   274.8   727.1   301.3  720.76   307.8  720.19     316  720.71
   320.2  722.54   324.3  726.69   336.7  746.18   344.9  752.37   377.9   766.2
   390.4  770.39   448.1  784.07   456.3  784.39   485.2  781.55     510  781.98
   530.6  786.91   551.2  789.56   571.9  794.04   592.5  800.37   612.5  800.36
#Mann= 5 ,-1,0
       0      .1       0  191.25     .05       0  286.25      .1       0
   301.3    .045       0     316      .1       0
Bank Sta=301.3,316
XS Rating Curve= 0 ,0
Exp/Cntr(USF)=0,0
Exp/Cntr=0.3,0.1

Type RM Length L Ch R = 1 ,1000    ,265.1,266,267.2
BEGIN DESCRIPTION:
Structure 2 XS 4
END DESCRIPTION:
XS GIS Cut Line= 6
1616076.35170484409806.687246338 1615998.5437896409754.390106842
1615863.67693333   409663.7413381615780.68234867409607.957328841
  1615718.435754409566.1198140831615568.00724909409465.011420503
#Sta/Elev= 30
       0  799.39    16.1  791.22      34  785.82    61.2  771.46    88.2  759.67
   128.5  732.64   140.1  726.63   145.8  725.35   154.5     725   211.8  725.45
   231.6  724.73   279.8   720.9   290.7  719.57   297.8  717.28   303.9  717.03
   310.1  717.28   318.4  718.31   321.7  720.52   332.8  732.64   342.5  741.89
   350.5  751.27   356.2  756.18   366.6  761.46   376.2  767.12     381  768.99
   402.4  771.37     463  789.41   520.8  803.46   549.4  809.74   612.5  826.59
#Mann= 7 ,-1,0
       0      .1       0  123.75     .06       0  241.25      .1       0
   297.8    .045       0   310.1      .1       0  451.25     .05       0
  481.25      .1       0
Bank Sta=297.8,310.1
XS Rating Curve= 0 ,0
Exp/Cntr(USF)=0,0
Exp/Cntr=0.3,0.1

Type RM Length L Ch R = 1 ,734     ,43.1,43.3,43.7
BEGIN DESCRIPTION:
Structure 2 XS 3
END DESCRIPTION:
XS GIS Cut Line= 6
1616295.17610677409770.2653948371616130.83769309409506.722694856
1616029.62927979409469.6463454291615997.56324786409439.584440488
1615945.45594596 409291.279042781615605.75642013409266.227455329
#Sta/Elev= 30
       0  760.48    58.7  754.26     101  746.47   128.3  742.61   157.6  735.63
   176.5  727.79   190.6  725.44     225  724.12     266  724.03   385.4  721.48
   423.3  719.44   426.2     719  435.56715.1586   440.3  714.52     446  715.13
   468.8  719.67   531.9  722.62   620.4  725.11   637.8  731.32   657.8  732.69
   662.2  734.05   670.8  742.03   677.9  746.53   705.5  759.04   721.3  767.08
     730  770.49   762.1  771.68   778.1   774.1   850.3  795.64     961  823.32
#Mann= 6 ,-1,0
       0     .05       0  435.56    .045       0     446     .05       0
  515.67      .1       0  690.37     .05       0  890.37      .1       0
Bank Sta=435.56,446
XS Rating Curve= 0 ,0
Exp/Cntr(USF)=0,0
Exp/Cntr=0.3,0.1

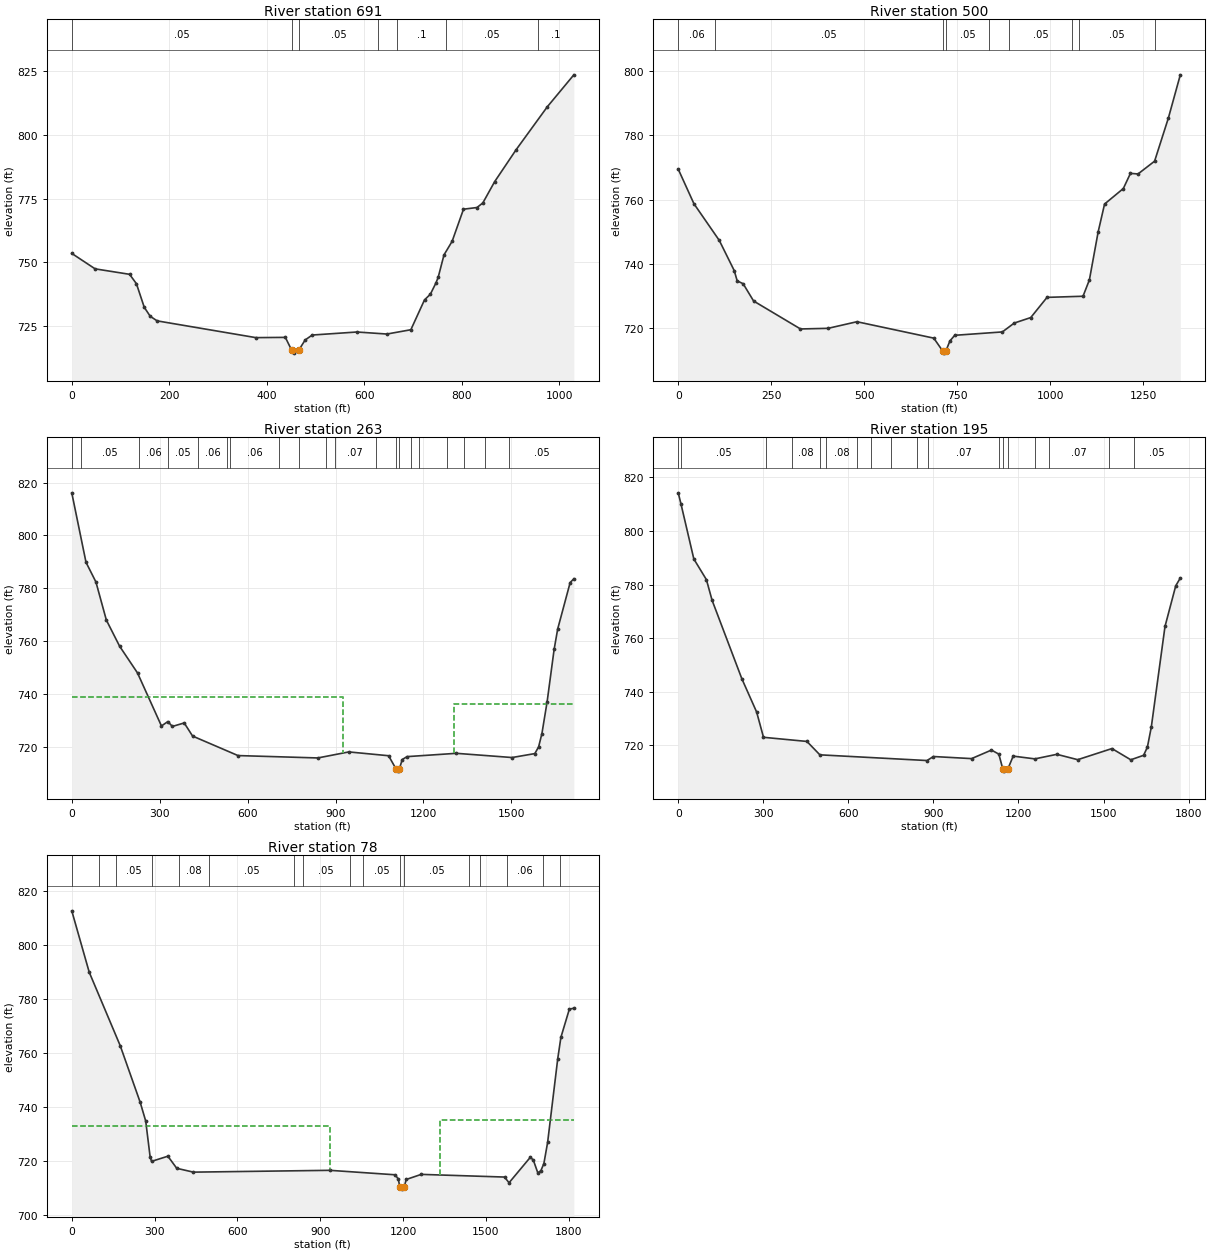
Type RM Length L Ch R = 1 ,691     ,191.4,190.6,189.8
BEGIN DESCRIPTION:
Structure 2 XS 2
END DESCRIPTION:
XS GIS Cut Line= 6
1616328.24420221409761.2468233551616150.87896305409475.658726417
1616056.68499424409436.5782499941616032.63547029409412.528726041
1615988.54467637409243.1799948741615605.75642013 409245.18412187
#Sta/Elev= 30
       0  753.52    47.9  747.46   118.6  745.32   132.7  741.62   148.7  732.38
   160.9  728.86   175.1  727.05   377.7  720.47   438.2  720.57  450.88  715.65
     456  714.39  466.03  715.65   478.9  719.57   493.4  721.49     585  722.68
   646.6  721.88   695.7  723.57   723.7  735.28   735.7   737.5   746.9  741.82
   751.7  744.09   763.7  752.94   780.4  758.28   803.7  770.87   831.4  771.53
   843.4  773.34   867.7   781.7   911.7  794.22   975.7  811.07  1030.1   823.6
#Mann= 7 ,-1,0
       0     .05       0  450.88    .045       0  466.03     .05       0
  628.99     .07       0  667.32      .1       0  767.32     .05       0
  957.32      .1       0
Bank Sta=450.88,466.03
XS Rating Curve= 0 ,0
Exp/Cntr(USF)=0,0
Exp/Cntr=0.3,0.1

Type RM Length L Ch R = 1 ,500     ,235.8,237,238.1
BEGIN DESCRIPTION:
Structure 1 XS 4
END DESCRIPTION:
XS GIS Cut Line= 6
1616435.92367522409854.7044541911616453.83804286409526.702031809
  1616328.182566409406.909502596  1615996.313151 409141.41397059
1615871.87530868409051.8204407171615608.84705614409106.127308372
#Sta/Elev= 30
       0  769.52    42.2  758.77   110.3  747.37   150.4     738   158.4   734.8
   174.4  733.91   202.5  728.54   328.5  719.85   402.7  720.05   480.1   722.1
   686.6     717  710.65712.9938   714.4  712.34     719 712.975     730  716.14
   742.9  717.88   870.9  718.93   902.9  721.69   947.1  723.39   990.9  729.67
  1087.6  730.02  1104.7  735.09  1128.2  749.99  1145.5  758.68  1195.9   763.5
    1215  768.21  1235.4  768.03  1279.9     772  1317.1  785.47    1349  798.84
#Mann= 9 ,-1,0
       0     .06       0     100     .05       0  710.65    .045       0
     719     .05       0   834.6     .07       0   889.6     .05       0
  1057.1     .07       0  1077.1     .05       0 1280.43      .1       0
Bank Sta=710.65,719
XS Rating Curve= 0 ,0
Exp/Cntr(USF)=0,0
Exp/Cntr=0.3,0.1

Type RM Length L Ch R = 1 ,263     ,68.1,68.2,68.6
BEGIN DESCRIPTION:
Structure 1 XS 3
END DESCRIPTION:
XS GIS Cut Line= 6
1616782.06502494410076.0748528761616679.63958372409587.226156164
1616567.90273876409424.2765905931616377.01896195409168.212987553
1616111.64395516408849.2974092221615923.08802929408639.790824917
#Sta/Elev= 30
       0   816.1    48.6  789.84    82.4  782.41     118  768.01   163.4   758.1
   224.3  748.03     306  727.99   327.8  729.64   343.3  727.81   383.7  729.13
   412.3  724.17   567.2   716.8   839.6   715.9   945.4  718.18    1081  716.74
  1106.2   711.8  1112.5  710.92 1117.97711.8176  1127.7  715.31  1144.1   716.4
  1312.3  717.65  1502.4  716.06  1580.1  717.55    1593  720.09  1604.3  725.14
    1622  737.12  1645.9  756.91  1658.1  764.65  1700.6  782.19  1713.2  783.62
#Mann= 20 ,-1,0
       0      .1       0      30     .05       0     230     .06       0
     330     .05       0     430     .06       0  529.46     .05       0
  539.46     .06       0  707.04     .05       0  777.04     .06       0
  867.04     .05       0  897.04     .07       0 1036.43     .05       0
  1106.2    .045       0 1117.97     .05       0 1156.43     .07       0
 1186.43     .06       0 1280.03     .07       0 1340.03     .05       0
 1410.03     .07       0 1491.32     .05       0
#XS Ineff= 2 , 0
          926.53   739.1 1305.68          736.21
Permanent Ineff=
       F       F
Bank Sta=1106.2,1117.97
XS Rating Curve= 0 ,0
Exp/Cntr(USF)=0,0
Exp/Cntr=0.3,0.1

Type RM Length L Ch R = 1 ,195     ,118,116.8,115.6
BEGIN DESCRIPTION:
Structure 1 XS 2
END DESCRIPTION:
XS GIS Cut Line= 4
1616828.62204367410055.1241944461616768.09791932409547.652690239
1616300.19988104408965.6899560581615960.33364427408581.594551499
#Sta/Elev= 30
       0  814.23      10  809.93      55  789.55    99.3  781.85   119.4  774.14
   224.2  744.89   276.5  732.44   300.7  723.01   453.8  721.47   499.5  716.47
   877.4  714.34     900  715.84  1034.5  715.06  1104.7  718.25  1130.7  716.73
  1144.9  711.09  1150.6  710.39  1162.2  711.12  1181.3  715.99  1257.8  714.96
  1335.2  716.66  1408.9  714.66  1529.6  718.81    1596  714.62  1641.2  716.29
  1654.6  719.34  1668.4  726.83  1716.7  764.37  1754.6  779.54  1770.7  782.45
#Mann= 18 ,-1,0
       0      .1       0      10     .05       0     310     .07       0
     400     .08       0     500     .05       0  521.07     .08       0
  631.07     .05       0  681.07     .06       0  751.07     .07       0
  841.07     .06       0  881.07     .07       0 1131.07     .05       0
  1144.9    .045       0  1162.2     .07       0  1257.8     .05       0
  1307.8     .07       0  1517.8     .06       0  1607.8     .05       0
Bank Sta=1144.9,1162.2
XS Rating Curve= 0 ,0
Exp/Cntr(USF)=0,0
Exp/Cntr=0.3,0.1

Type RM Length L Ch R = 1 ,78      ,,,
BEGIN DESCRIPTION:
Structure 1 XS 1
END DESCRIPTION:
XS GIS Cut Line= 4
1616875.17906241410043.4849397621616837.93344742409598.865410847
1616519.01786909409030.8697822871615992.92355739408537.365383701
#Sta/Elev= 30
       0  812.53    63.2  789.81   175.6  762.58   247.8  741.67   267.9  734.69
   283.9  721.41     289  719.77   348.2  721.69   380.3  717.21   440.5  715.79
   935.1  716.46  1171.1  714.81  1182.8  713.28  1188.7  710.16  1194.7   709.5
 1203.86 710.148  1211.6  713.07  1266.1  714.96  1567.7  713.97  1584.2  711.86
    1661  721.26  1671.9  720.32  1688.4  715.51  1699.4  716.33  1710.3  718.94
  1723.9  726.79  1760.6  757.82    1772  765.69  1802.6  776.12  1818.9  776.48
#Mann= 17 ,-1,0
       0     .05       0     100     .06       0     160     .05       0
     290     .07       0     390     .08       0  496.18     .05       0
  806.18     .07       0  836.18     .05       0 1006.18     .07       0
 1056.18     .05       0  1188.7    .045       0 1203.86     .05       0
 1437.58     .07       0 1477.58     .05       0 1577.58     .06       0
 1707.58     .05       0 1767.58     .06       0
#XS Ineff= 2 , 0
          936.02  732.69 1334.29          735.17
Permanent Ineff=
       F       F
Bank Sta=1188.7,1203.86
XS Rating Curve= 0 ,0
Exp/Cntr(USF)=0,0
Exp/Cntr=0.3,0.1
LCMann Table=0

Chan Stop Cuts=-1
Use User Specified Reach Order=0
Composite Channel Slope=5